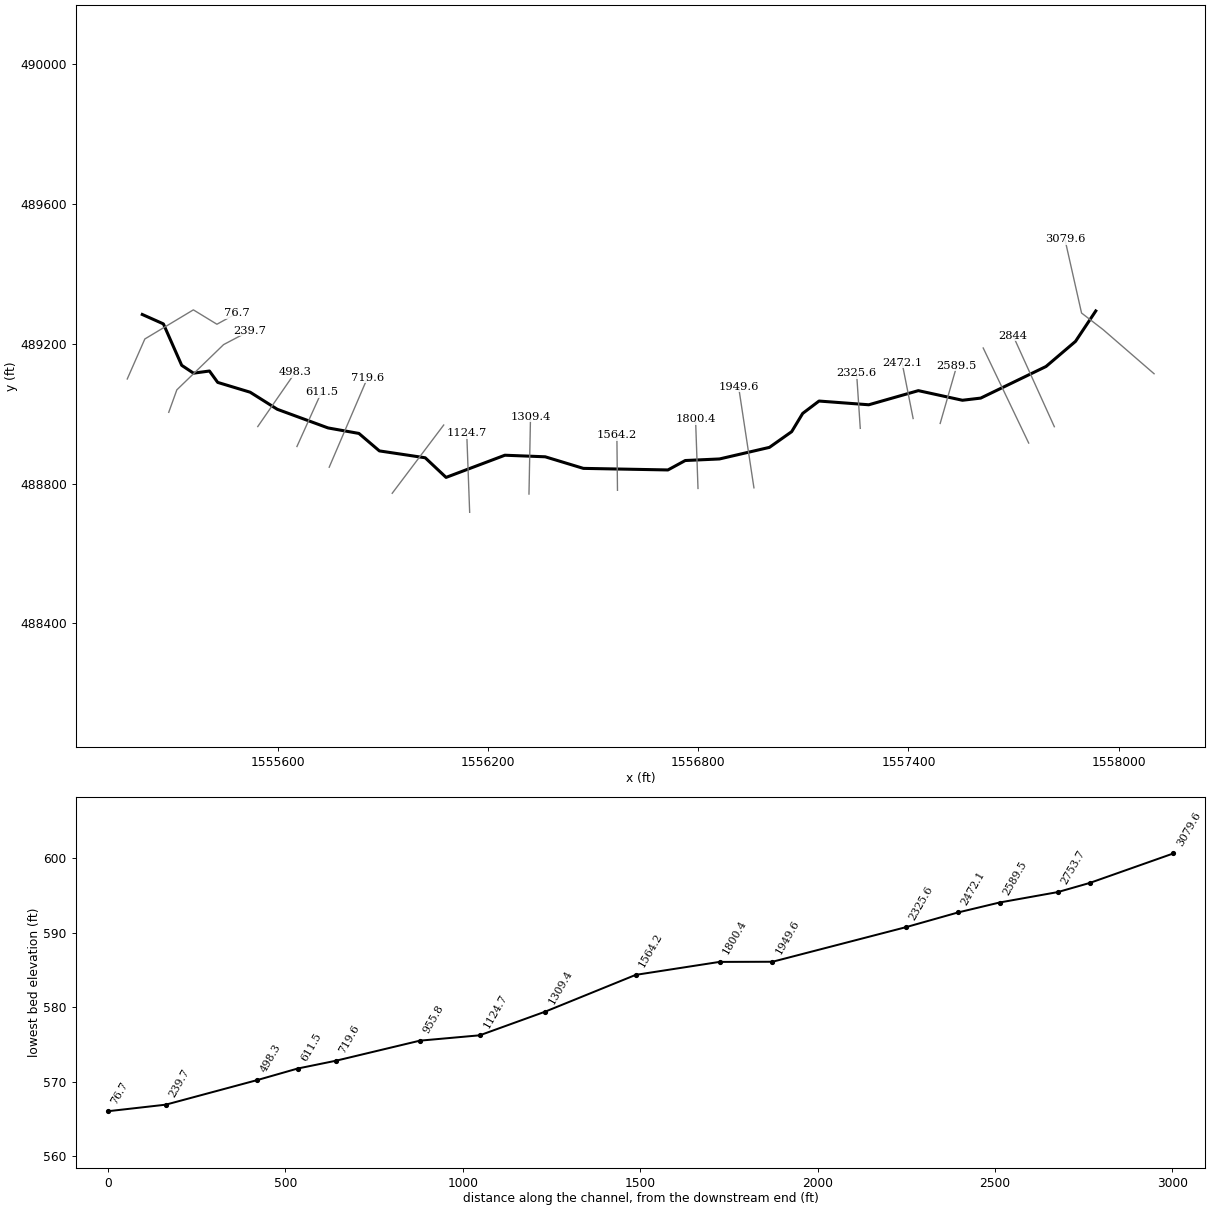
--- NP39.prj (project) ---

Proj Title=NP39
Current Plan=p01
Default Exp/Contr=0,0
English Units
Geom File=g01
Flow File=f01
Plan File=p01
BEGIN DESCRIPTION:
END DESCRIPTION:
DSS Export Rating Curves= 0
DSS Export Rating Curve Sorted= 0
DSS Export Volume Flow Curves= 0
DXF OffsetX= 0
DXF OffsetY= 0
DXF ScaleX= 0
DXF ScaleY= 0

--- NP39.p01 (plan) ---

Plan Title=Floodplain
Program Version=4.00
Geom File=g01
Flow File=f01
K Sum by GR=0
Std Step Tol=0.01
Critical Tol=0.01
Num of Std Step Trials=20
Max Error Tol=0.3
Flow Tol Ratio=0.001
Split Flow NTrial=30
Split Flow Tol=0.02
Split Flow Ratio=0.02
Log Output Level=0
Friction Slope Method=1
Unsteady Friction Slope Method=2
Unsteady Bridges Friction Slope Method=1
Global Log Level=0
CheckData=False
Run HTab=0
Run UNet=0
Run PostProcess=0
UNET Theta=0
UNET Theta Warmup=0
UNET ZTol=0
UNET ZSATol=0
UNET MxIter=0
UNET MaxInSteps=0
UNET DtIC=0
UNET DtMin=0
UNET MaxCRTS=0
UNET WFStab=0
UNET SFStab=0
UNET WFX=0
UNET SFX=0
UNET DSS MLevel=0
UNET DZMax Abort=0
UNET Convert EG Bridges=0
UNET Use Existing IB Tables=0
UNET Froude Limit=0
UNET Froude Power=0
Write IC File=0
Echo Input=False
Echo Output=False
Write Detailed=0

--- NP39.f01 (steady flow) ---

Flow Title=NFF Regression Equation
Program Version=4.00
Number of Profiles= 1
Profile Names=P100yr
River Rch & RM=NP39,Main            ,3079.6
383.9423
River Rch & RM=NP39,Main            ,2325.6
409.6379
River Rch & RM=NP39,Main            ,239.7
 449.682
Boundary for River Rch & Prof#=NP39,Main            , 1
Up Type= 0
Dn Type= 3
Dn Slope=0.010593
DSS Import GetInterval= 0
DSS Import GetPeak= 0
DSS Import FillOption= 0

--- NP39.g01 (geometry) ---

Geom Title=Geometry
Program Version=4.00

River Reach=NP39            ,Main
Reach XY= 30
     1557934.501      489293.421     1557876.694      489206.429
     1557792.508      489134.591     1557606.178      489044.232
     1557553.983      489038.059     1557428.266      489065.559
     1557286.834       489025.15     1557144.842      489035.814
     1557098.259      489000.456      1557066.83      488948.261
      1557003.41      488903.362     1556860.856      488870.249
     1556763.201      488865.759     1556713.812       488838.82
     1556472.481       488843.31     1556363.601      488876.423
     1556248.547      488880.912     1556080.738      488817.493
     1556021.247      488873.616     1555890.479       488893.26
      1555832.11       488943.21     1555743.996      488958.924
     1555599.197      489012.242     1555521.746       489061.07
     1555429.142      489089.131      1555405.57      489121.683
      1555360.11      489115.509     1555326.436      489137.959
     1555274.241       489256.38     1555214.002      489283.312

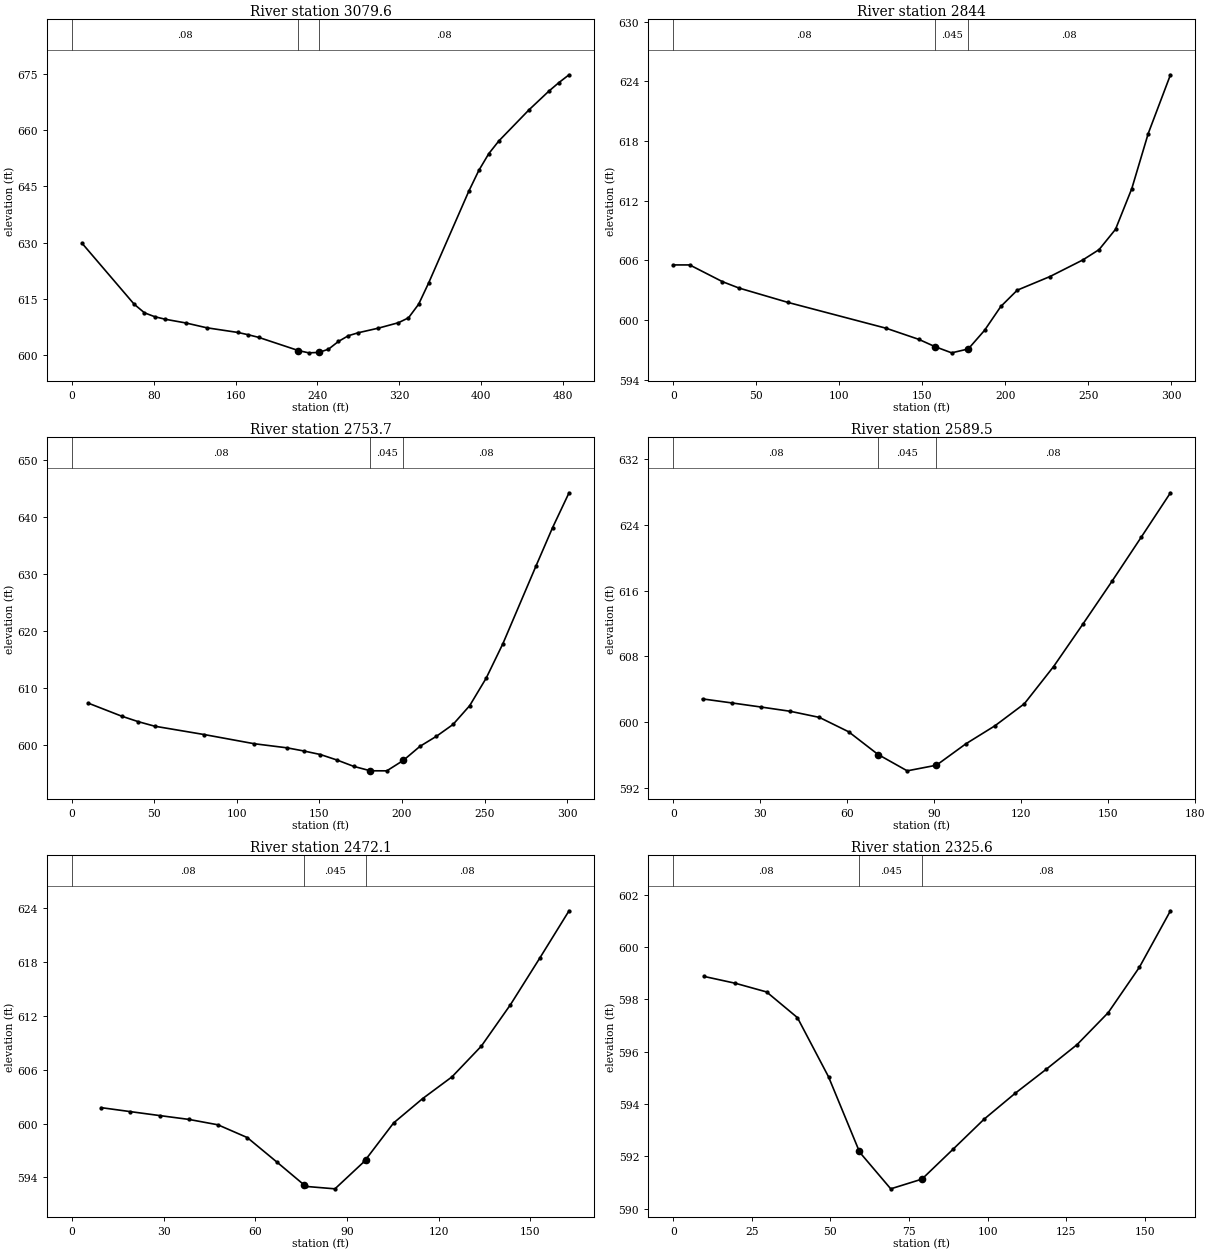
Type RM Length L Ch R = 1 ,3079.6  ,248.1,235.6,223.1
XS GIS Cut Line= 4
     1558100.835       489113.87     1557955.275      489240.139
     1557893.894       489287.49     1557846.543      489497.938
#Sta/Elev= 30
    10.1  629.82    60.9  613.62      71  611.32    81.1  610.28    91.3  609.61
   111.6  608.61   131.8  607.34   162.3  606.09   172.4  605.48   182.6  604.78
   221.5  601.26   231.5  600.66   241.5  600.77   250.8  601.63   260.5  603.69
   270.2  605.22     280  606.02   299.6  607.24   319.2  608.69     329  609.99
   338.9  613.61   348.7  619.28   387.9  643.71   397.7  649.25   407.5  653.75
   417.3  657.12   446.7  665.39   466.3  670.42   476.1  672.69   485.9  674.75
#Mann= 3 , 0 , 0
       0     .08       0   221.5    .045       0   241.5     .08       0
Bank Sta=221.5,241.5
XS Rating Curve= 0 ,0
Exp/Cntr=0.3,0.1

Type RM Length L Ch R = 1 ,2844    ,89.8,90.3,90.8
XS GIS Cut Line= 2
     1557816.257      488962.418     1557698.367      489223.117
#Sta/Elev= 20
       0  605.54     9.9  605.54    29.6  603.86    39.5  603.22    69.1  601.77
   128.3  599.17     148  598.05   157.7  597.32   167.7   596.7   177.7  597.09
   187.5  598.96   197.3  601.36   207.2     603   226.9  604.37   246.7  606.04
   256.5  607.08   266.4  609.12   276.2  613.21   286.1  618.75   299.5  624.66
#Mann= 3 , 0 , 0
       0     .08       0   157.7    .045       0   177.7     .08       0
Bank Sta=157.7,177.7
XS Rating Curve= 0 ,0
Exp/Cntr=0.3,0.1

Type RM Length L Ch R = 1 ,2753.7  ,182.4,164.2,146
XS GIS Cut Line= 2
     1557743.073      488915.698     1557613.296      489187.527
#Sta/Elev= 23
      10  607.34    30.1  605.07    40.2   604.1    50.2   603.3    80.3  601.83
   110.4  600.23   130.5   599.5   140.6  598.95   150.6  598.33   160.7  597.36
   170.7  596.26   180.8  595.48   190.8  595.47   200.8   597.3   210.9  599.77
   220.9  601.54   230.9   603.6     241   606.9     251  611.73   261.1  617.76
   281.1  631.35   291.2  638.12   301.2  644.25
#Mann= 3 , 0 , 0
       0     .08       0   180.8    .045       0   200.8     .08       0
Bank Sta=180.8,200.8
XS Rating Curve= 0 ,0
Exp/Cntr=0.3,0.1

Type RM Length L Ch R = 1 ,2589.5  ,105.4,117.4,129.3
XS GIS Cut Line= 2
     1557490.535      488971.817     1557537.886      489136.668
#Sta/Elev= 19
    10.1  602.82    20.2  602.33    30.3  601.83    40.4  601.31    50.4  600.57
    60.5  598.82    70.6  596.07    70.7  596.05    80.7  594.07    90.7  594.75
    90.8  594.76   100.9  597.35     111  599.56   121.1  602.23   131.2  606.76
   141.2  611.87   151.3  617.11   161.4  622.48   171.5  627.89
#Mann= 3 , 0 , 0
       0     .08       0    70.7    .045       0    90.7     .08       0
Bank Sta=70.7,90.7
XS Rating Curve= 0 ,0
Exp/Cntr=0.3,0.1

Type RM Length L Ch R = 1 ,2472.1  ,149.7,146.5,143.3
XS GIS Cut Line= 2
     1557413.371      488985.847     1557381.803      489145.437
#Sta/Elev= 19
     9.6  601.77    19.1  601.33    28.7  600.89    38.3  600.46    47.8  599.86
    57.4  598.44      67  595.74    76.1  593.14    76.6     593    86.1  592.73
    95.7  595.78    96.1  595.96   105.3  600.07   114.8  602.78   124.4   605.2
     134  608.62   143.5  613.22   153.1  618.41   162.7  623.69
#Mann= 3 , 0 , 0
       0     .08       0    76.1    .045       0    96.1     .08       0
Bank Sta=76.1,96.1
XS Rating Curve= 0 ,0
Exp/Cntr=0.3,0.1

Type RM Length L Ch R = 1 ,2325.6  ,373.8,376,378.2
XS GIS Cut Line= 2
     1557262.549      488957.788     1557252.027      489115.624
#Sta/Elev= 18
     9.9  598.87    19.8  598.61    29.7  598.28    39.5   597.3    49.4  595.04
    59.2  592.19    59.3  592.16    69.2  590.76    79.1  591.13    79.2  591.14
      89  592.27    98.9  593.42   108.8  594.41   118.6  595.32   128.5  596.27
   138.4  597.49   148.3  599.22   158.2  601.38
#Mann= 3 , 0 , 0
       0     .08       0    59.2    .045       0    79.2     .08       0
Bank Sta=59.2,79.2
XS Rating Curve= 0 ,0
Exp/Cntr=0.3,0.1

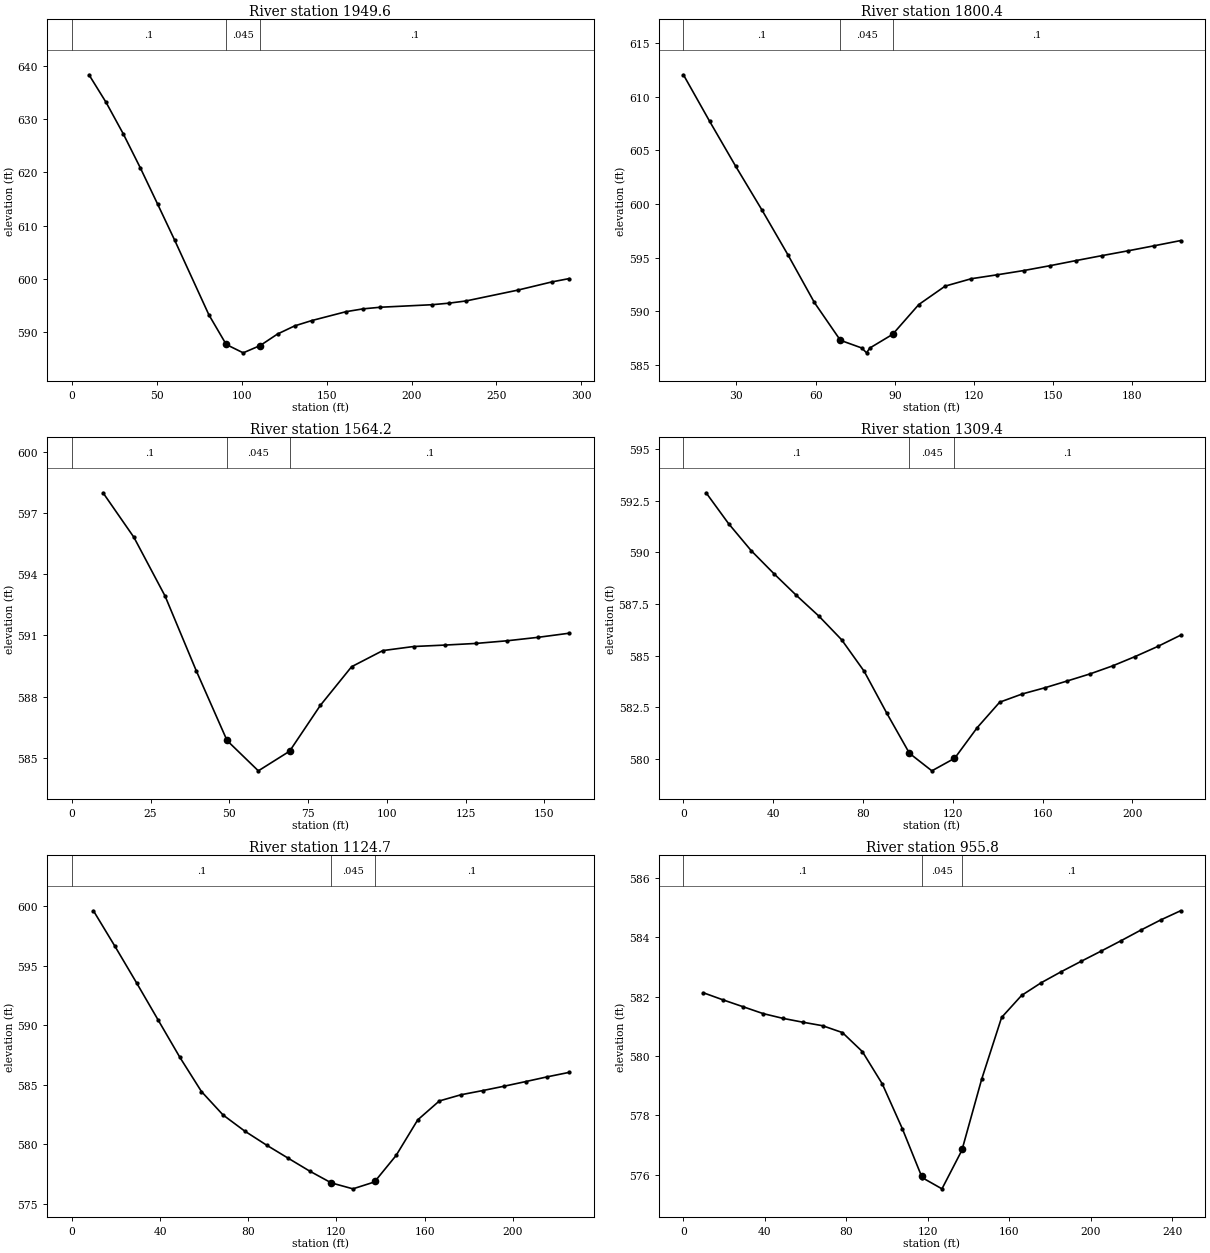
Type RM Length L Ch R = 1 ,1949.6  ,152.1,149.2,146.3
XS GIS Cut Line= 2
     1556959.153      488787.675      1556915.31      489077.041
#Sta/Elev= 22
    10.1  638.31    20.2  633.11    30.3  627.21    40.4  620.79    50.5  614.04
    60.6  607.23    80.7  593.25    90.9  587.69   100.9  586.12   110.9  587.49
   121.1  589.65   131.2  591.18   141.3  592.18   161.5  593.85   171.6  594.38
   181.7  594.68   211.9  595.15     222  595.44   232.1  595.86   262.4  597.88
   282.6  599.43   292.7  600.05
#Mann= 3 , 0 , 0
       0      .1       0    90.9    .045       0   110.9      .1       0
Bank Sta=90.9,110.9
XS Rating Curve= 0 ,0
Exp/Cntr=0.3,0.1

Type RM Length L Ch R = 1 ,1800.4  ,236.7,236.2,235.8
XS GIS Cut Line= 2
     1556799.563      488785.921     1556792.548      488984.093
#Sta/Elev= 24
     9.9  612.06    19.8  607.73    29.7  603.52    39.7  599.42    49.6  595.21
    59.5  590.81    69.3   587.3    69.4  587.27   77.52  586.55    79.3   586.1
   80.54  586.55    89.2  587.83    89.3  587.86    99.1  590.61   109.1  592.33
     119  593.02   128.9  593.39   138.8  593.78   148.7  594.23   158.6  594.71
   168.6  595.18   178.5  595.63   188.4   596.1   198.3  596.58
#Mann= 3 , 0 , 0
     9.9      .1       0    69.3    .045       0    89.3      .1       0
Bank Sta=69.3,89.3
XS Rating Curve= 0 ,0
Exp/Cntr=0.3,0.1

Type RM Length L Ch R = 1 ,1564.2  ,255.7,254.8,254
XS GIS Cut Line= 2
     1556569.824       488780.66      1556568.07      488938.496
#Sta/Elev= 18
     9.9  597.98    19.7   595.8    29.6  592.92    39.5  589.26    49.2  585.87
    49.3  585.84    59.2  584.36    69.1  585.32    69.2  585.34    78.9  587.57
    88.8  589.46    98.7  590.25   108.5  590.45   118.4  590.52   128.2   590.6
   138.1  590.73     148   590.9   157.8   591.1
#Mann= 3 , 0 , 0
       0      .1       0    49.2    .045       0    69.2      .1       0
Bank Sta=49.2,69.2
XS Rating Curve= 0 ,0
Exp/Cntr=0.3,0.1

Type RM Length L Ch R = 1 ,1309.4  ,183.1,184.7,186.3
XS GIS Cut Line= 2
     1556317.286      488769.919     1556321.671      488991.328
#Sta/Elev= 23
    10.1  592.88    20.1  591.39    30.2  590.08    40.3  588.97    50.3  587.92
    60.4  586.91    70.5  585.77    80.5  584.25    90.6  582.22   100.7  580.28
   110.7  579.43   120.7  580.03   120.8  580.03   130.9  581.52   140.9  582.75
     151  583.15   161.1  583.45   171.1  583.78   181.2  584.12   191.3  584.51
   201.3  584.96   211.4  585.45   221.5  585.99
#Mann= 3 , 0 , 0
       0      .1       0   100.7    .045       0   120.7      .1       0
Bank Sta=100.7,120.7
XS Rating Curve= 0 ,0
Exp/Cntr=0.3,0.1

Type RM Length L Ch R = 1 ,1124.7  ,187.5,168.9,150.5
XS GIS Cut Line= 2
     1556148.075      488717.722     1556139.721        488943.1
#Sta/Elev= 25
     9.8  599.63    19.6  596.63    29.4  593.56    39.2  590.43      49  587.31
    58.8  584.43    68.6  582.46    78.4  581.11    88.3  579.93    98.1  578.83
   107.9  577.74   117.5  576.77   117.7  576.75   127.5  576.25   137.3  576.83
   137.5  576.88   147.1  579.06   156.9  582.05   166.7  583.64   176.5  584.16
   186.3  584.51   196.1  584.88   205.9  585.27   215.7  585.67   225.5  586.04
#Mann= 3 , 0 , 0
       0      .1       0   117.5    .045       0   137.5      .1       0
Bank Sta=117.5,137.5
XS Rating Curve= 0 ,0
Exp/Cntr=0.3,0.1

Type RM Length L Ch R = 1 ,955.8   ,228.7,236.2,243.4
XS GIS Cut Line= 2
      1555927.08      488772.111     1556073.955      488967.214
#Sta/Elev= 27
     9.8  582.13    19.5  581.89    29.3  581.66    39.1  581.43    48.8  581.27
    58.6  581.14    68.4  581.02    78.1  580.79    87.9  580.15    97.7  579.06
   107.5  577.56     117  575.95   117.2  575.91     127  575.53   136.8  576.83
     137  576.88   146.5  579.22   156.3   581.3   166.1  582.04   175.8  582.47
   185.6  582.84   195.4  583.19   205.1  583.53   214.9  583.88   224.7  584.24
   234.4  584.58   244.2  584.89
#Mann= 3 , 0 , 0
       0      .1       0     117    .045       0     137      .1       0
Bank Sta=117,137
XS Rating Curve= 0 ,0
Exp/Cntr=0.3,0.1

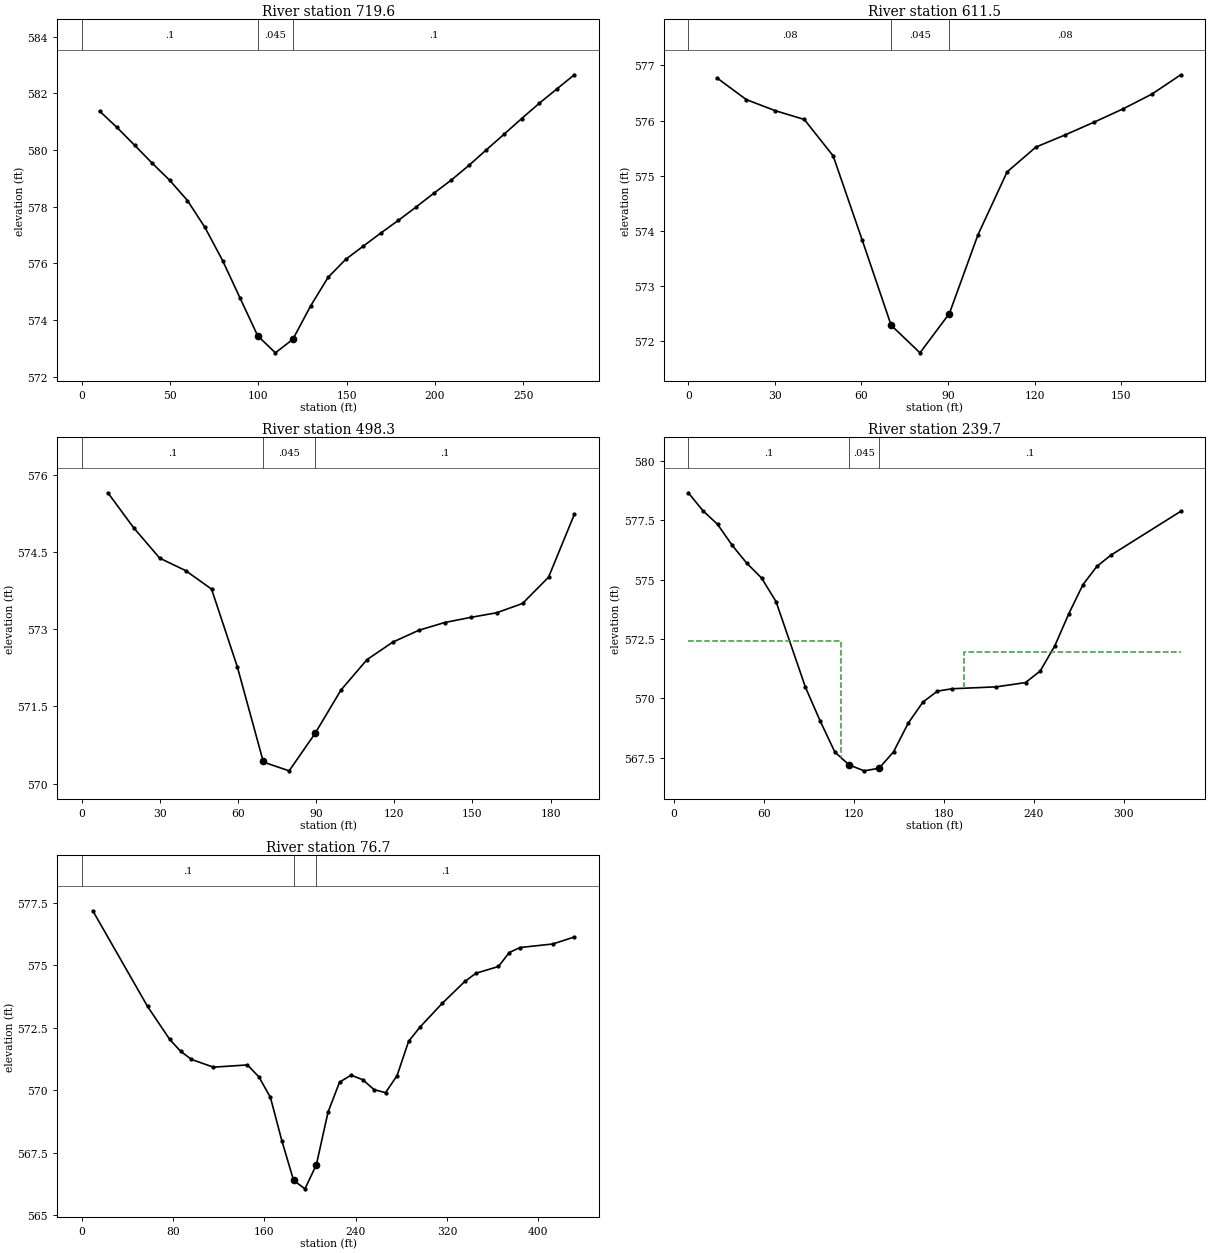
Type RM Length L Ch R = 1 ,719.6   ,108.7,108.1,107.5
XS GIS Cut Line= 2
     1555747.322      488846.645     1555856.931      489103.128
#Sta/Elev= 29
      10  581.38    19.9   580.8    29.9  580.17    39.8  579.54    49.8  578.93
    59.8  578.22    69.7  577.27    79.7   576.1    89.7  574.76    99.6  573.44
   109.6  572.84   119.5  573.32   119.6  573.33   129.5  574.49   139.5  575.51
   149.4  576.14   159.4  576.61   169.3  577.07   179.3  577.52   189.3  577.99
   199.2  578.47   209.2  578.94   219.2  579.46   229.1  580.01   239.1  580.56
     249  581.11     259  581.65     269  582.16   278.9  582.66
#Mann= 3 , 0 , 0
       0      .1       0    99.6    .045       0   119.6      .1       0
Bank Sta=99.6,119.6
XS Rating Curve= 0 ,0
Exp/Cntr=0.3,0.1

Type RM Length L Ch R = 1 ,611.5   ,117.6,113.2,108.7
XS GIS Cut Line= 2
     1555655.251      488905.833     1555725.401      489061.477
#Sta/Elev= 18
      10  576.77    20.1  576.38    30.1  576.18    40.2  576.02    50.2  575.36
    60.3  573.83    70.3  572.29    80.3  571.79    90.3  572.49    90.4  572.49
   100.4  573.93   110.5  575.07   120.5  575.52   130.6  575.74   140.6  575.97
   150.6  576.21   160.7  576.48   170.7  576.83
#Mann= 3 , 0 , 0
       0     .08       0    70.3    .045       0    90.3     .08       0
Bank Sta=70.3,90.3
XS Rating Curve= 0 ,0
Exp/Cntr=0.3,0.1

Type RM Length L Ch R = 1 ,498.3   ,263.6,258.6,237.2
XS GIS Cut Line= 2
     1555543.451       488962.83     1555650.867      489118.474
#Sta/Elev= 20
      10  575.65    19.9  574.97    29.9  574.38    39.8  574.14    49.8  573.78
    59.7  572.27    69.6  570.44    69.7  570.42    79.6  570.25    89.6  570.98
    99.5  571.82   109.5  572.41   119.4  572.75   129.4  572.98   139.3  573.13
   149.3  573.23   159.3  573.32   169.2   573.5   179.2  574.01   189.1  575.23
#Mann= 3 , 0 , 0
       0      .1       0    69.6    .045       0    89.6      .1       0
Bank Sta=69.6,89.6
XS Rating Curve= 0 ,0
Exp/Cntr=0.3,0.1

Type RM Length L Ch R = 1 ,239.7   ,168.4,163,172.8
XS GIS Cut Line= 4
     1555289.487      489003.583     1555312.562       489067.79
     1555445.992      489197.207     1555520.231      489236.333
#Sta/Elev= 27
     9.7  578.66    19.5   577.9    29.2  577.33      39  576.44    48.7  575.69
    58.5  575.07    68.2  574.07    87.8  570.46    97.6  569.04   107.4  567.73
   116.9  567.19   126.9  566.94   136.9  567.05   146.5  567.74   156.3  568.95
   166.1  569.84   175.8   570.3   185.6   570.4     215  570.48   234.5  570.66
   244.3  571.15   254.1  572.22   263.4  573.57   272.8  574.79   282.1  575.56
   291.4  576.03     338  577.88
#Mann= 3 , 0 , 0
     9.7      .1       0   116.9    .045       0   136.9      .1       0
#XS Ineff= 2 , 0
          111.54   572.4  193.71          571.95
Permanent Ineff=
       F       F
Bank Sta=116.9,136.9
XS Rating Curve= 0 ,0
Exp/Cntr=0.3,0.1

Type RM Length L Ch R = 1 ,76.7    ,58.1,76.7,95.3
XS GIS Cut Line= 5
     1555171.106       489098.89     1555221.268      489213.259
     1555359.714      489296.527      1555426.93      489255.394
     1555485.118      489287.498
#Sta/Elev= 30
     9.6  577.19    57.6  573.36    76.9  572.05    86.5  571.57    96.1  571.24
   115.3  570.93   145.1  571.02   155.2  570.54   165.3  569.72   175.4  567.97
   185.6   566.4   195.6  566.06   205.6  567.03   215.8  569.13   225.9  570.33
     236  570.61   246.1  570.43   256.2  570.03   266.2  569.91   276.3  570.59
   286.4  571.96   296.3  572.53     316  573.49   335.7  574.36   345.5  574.69
   365.2  574.96   374.7  575.52   384.2  575.72   412.7  575.86   431.7  576.14
#Mann= 3 , 0 , 0
       0      .1       0   185.6    .045       0   205.6      .1       0
Bank Sta=185.6,205.6
XS Rating Curve= 0 ,0
Exp/Cntr=0.3,0.1

Chan Stop Cuts=-1
Use User Specified Reach Order=0